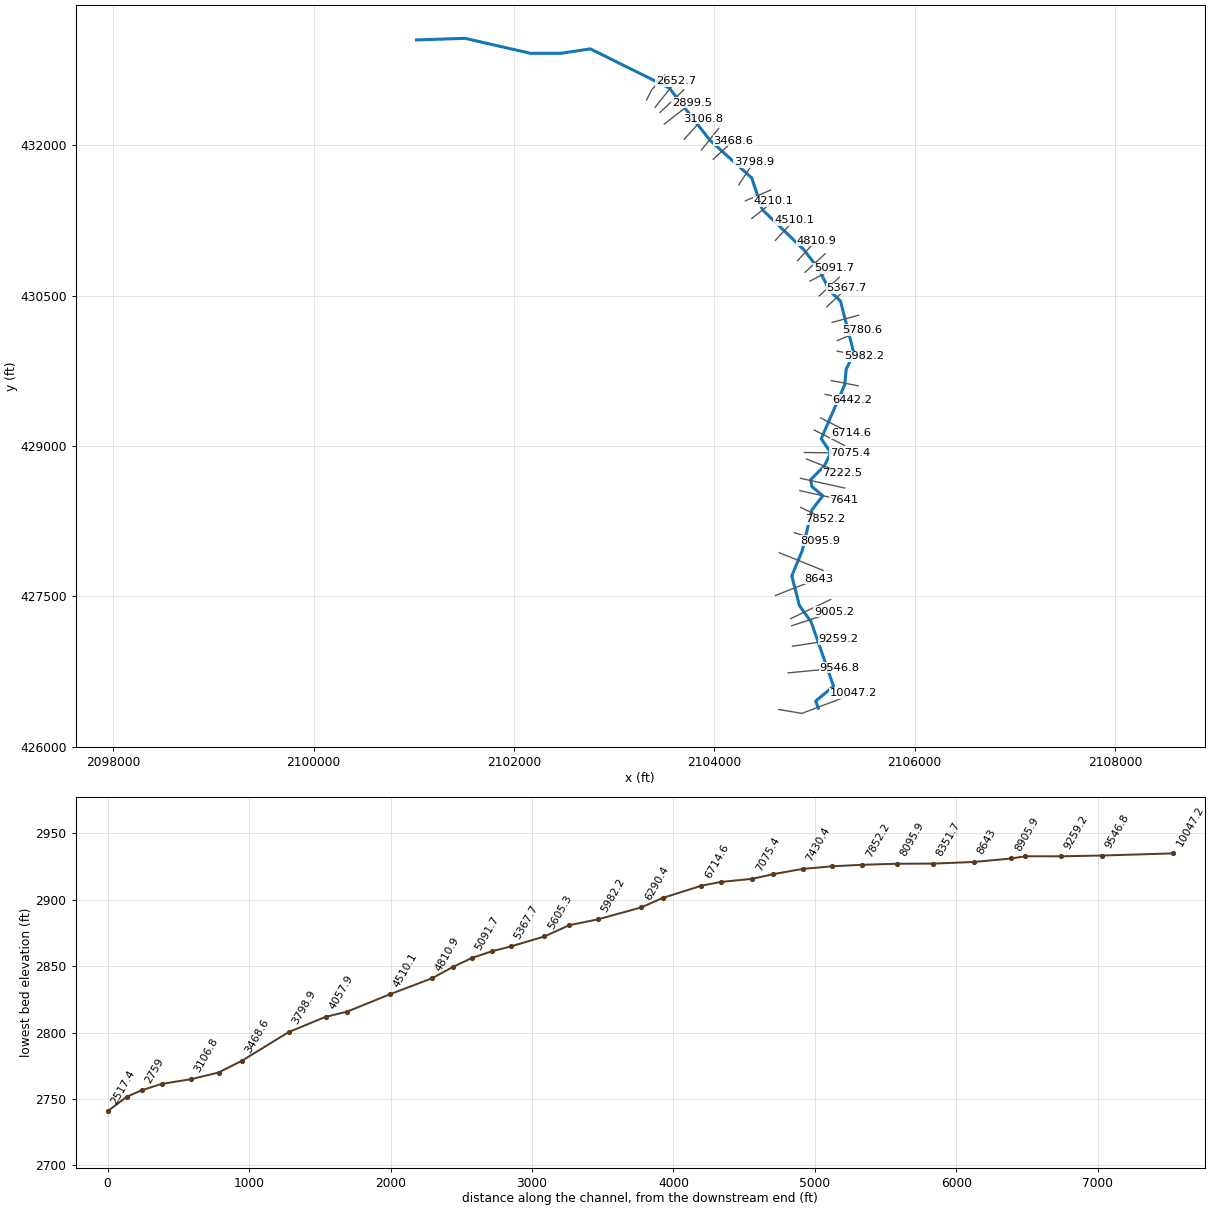
--- ImprvmntBr.prj (project) ---

Proj Title=ImprvmntBr
Current Plan=p01
Default Exp/Contr=0,0
English Units
Geom File=g01
Flow File=f01
Plan File=p01
BEGIN DESCRIPTION:
END DESCRIPTION:
DSS Export Rating Curves= 0
DSS Export Rating Curve Sorted= 0
DSS Export Volume Flow Curves= 0
DXF OffsetX= 0
DXF OffsetY= 0
DXF ScaleX= 0
DXF ScaleY= 0

--- ImprvmntBr.p01 (plan) ---

Plan Title=Floodplain
Program Version=4.00
Geom File=g01
Flow File=f01
K Sum by GR=0
Std Step Tol=0.01
Critical Tol=0.01
Num of Std Step Trials=20
Max Error Tol=0.3
Flow Tol Ratio=0.001
Split Flow NTrial=30
Split Flow Tol=0.02
Split Flow Ratio=0.02
Log Output Level=0
Friction Slope Method=1
Unsteady Friction Slope Method=2
Unsteady Bridges Friction Slope Method=1
Global Log Level=0
CheckData=False
Run HTab=0
Run UNet=0
Run PostProcess=0
UNET Theta=0
UNET Theta Warmup=0
UNET ZTol=0
UNET ZSATol=0
UNET MxIter=0
UNET MaxInSteps=0
UNET DtIC=0
UNET DtMin=0
UNET MaxCRTS=0
UNET WFStab=0
UNET SFStab=0
UNET WFX=0
UNET SFX=0
UNET DSS MLevel=0
UNET DZMax Abort=0
UNET Convert EG Bridges=0
UNET Use Existing IB Tables=0
UNET Froude Limit=0
UNET Froude Power=0
Write IC File=0
Echo Input=False
Echo Output=False
Write Detailed=0

--- ImprvmntBr.f01 (steady flow) ---

Flow Title=NFF Regression Equation
Program Version=4.00
Number of Profiles=1
Profile Names=P100yr
River Rch & RM=ImprvmntBr,Main      ,10047.2
578.2807
River Rch & RM=ImprvmntBr,Main      ,8905.9
588.3161
River Rch & RM=ImprvmntBr,Main      ,6851.8
649.6235
River Rch & RM=ImprvmntBr,Main      ,4810.9
705.6902
River Rch & RM=ImprvmntBr,Main      ,280.1
783.1192
Boundary for River Rch & Prof#=ImprvmntBr,Main      ,1
Up Type=0
Dn Type=3
Dn Slope=0.04127

--- ImprvmntBr.g01 (geometry) ---

Geom Title=USGS 10m DEM
Program Version=4.00

River Reach=ImprvmntBr      ,Main
Reach XY= 30
     2105037.085      426385.239     2105011.438      426456.746
      2105189.58      426604.642      2104965.57      427246.626
     2104848.501      427410.271     2104772.973      427704.832
     2104877.454      427957.852     2104973.123      428361.929
     2105082.639      428505.434     2104974.385      428595.011
      2104959.69       428665.22     2105096.737      428799.844
     2105161.944      428934.687     2105066.275      429073.156
     2105300.614      429610.791     2105316.172      429766.202
     2105392.306      429927.886     2105258.872      430446.515
     2105149.356      430552.255     2105043.676      430764.295
     2104890.258      430961.637     2104478.023      431359.293
     2104372.672      431675.112     2103953.903      432053.221
     2103550.063      432572.345      2102761.98      432962.674
     2102470.613      432918.814     2102162.205      432918.814
     2101509.788      433067.876     2101025.892      433051.663

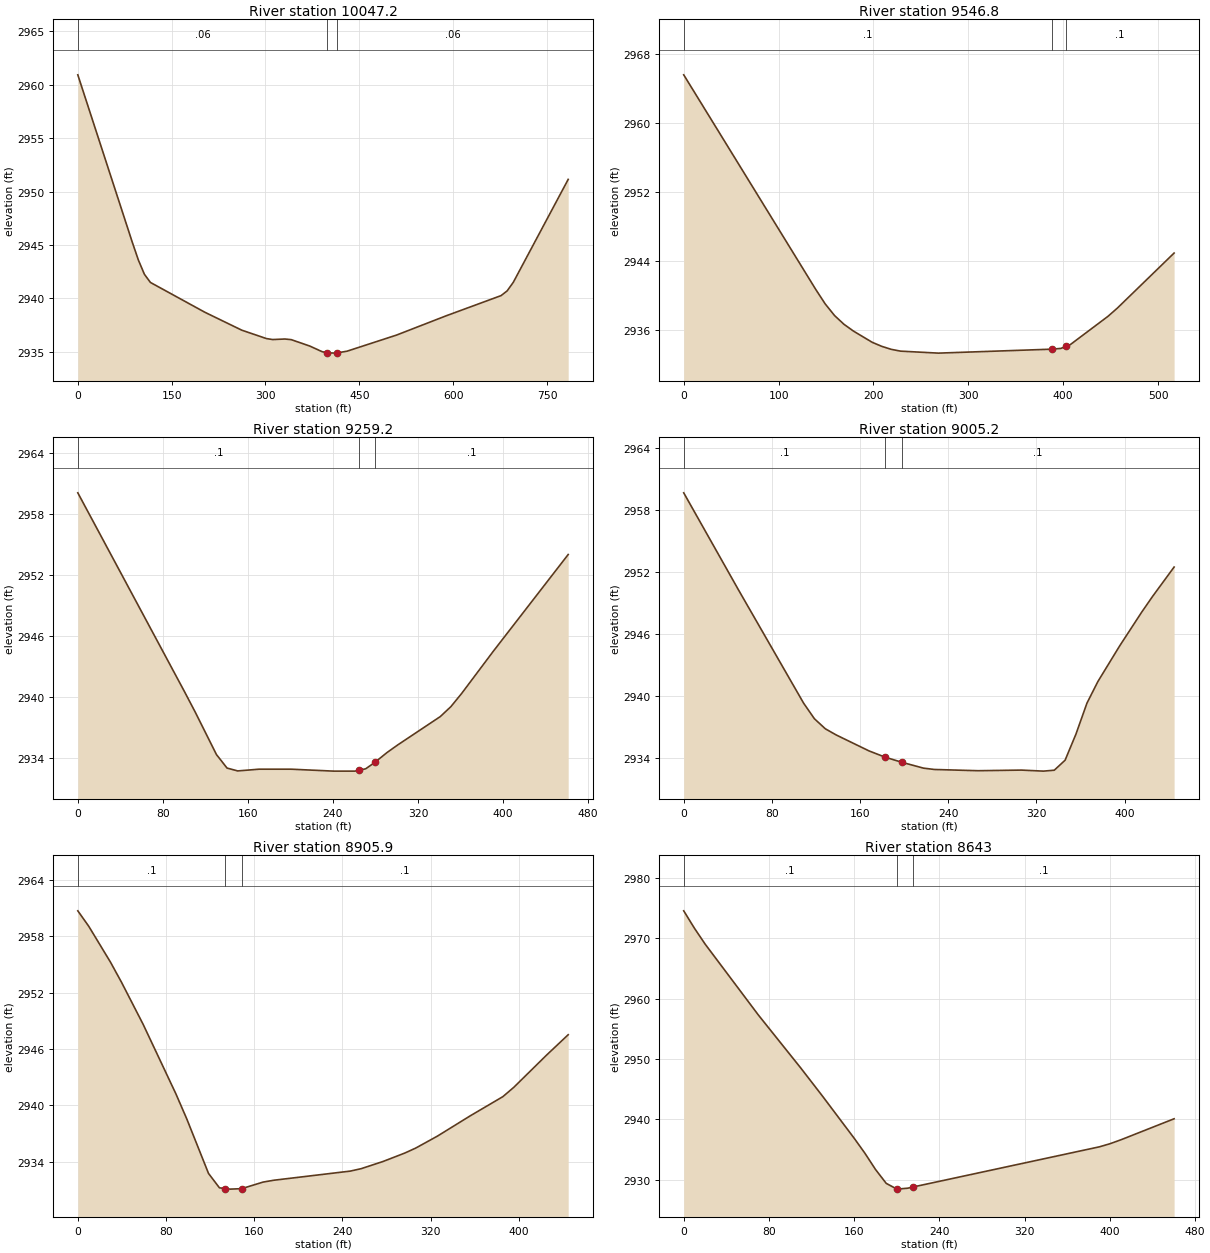
Type RM Length L Ch R = 1 ,10047.2 ,505.8,500.5,500.9
XS GIS Cut Line= 4
     2104643.397      426372.452     2104872.434      426333.802
     2105206.236      426459.001     2105387.002      426532.413
#Sta/Elev= 23
       0 2960.92    87.1 2945.26    96.8  2943.6   106.5 2942.26   116.1  2941.5
   203.2 2938.71     262 2937.04   301.6 2936.25   311.5 2936.16   331.3 2936.21
   341.2 2936.15   370.9 2935.55   390.7 2935.02   398.6 2934.93   410.5 2934.89
   413.6  2934.9   430.3 2935.07   509.6 2936.58   588.8 2938.38   676.6 2940.27
   686.3 2940.71   696.1 2941.51   783.9 2951.14
#Mann= 3 , 0 , 0
       0     .06       0   398.6    .045       0   413.6     .06       0
Bank Sta=398.6,413.6
XS Rating Curve= 0 ,0
Exp/Cntr=0.3,0.1

Type RM Length L Ch R = 1 ,9546.8  ,286.1,287.5,289.1
XS GIS Cut Line= 2
     2104736.348      426737.769     2105250.819      426787.487
#Sta/Elev= 18
       0 2965.61   139.2 2940.69   149.1 2939.02     159 2937.66     169 2936.64
   178.9 2935.86   198.8 2934.55   208.7 2934.09   218.7 2933.74   228.6 2933.53
   268.4  2933.3   388.2 2933.76   397.6 2933.85   403.2  2934.1   407.5 2934.29
   447.3 2937.58   457.2 2938.54   516.9 2944.92
#Mann= 3 , 0 , 0
       0      .1       0   388.2    .045       0   403.2      .1       0
Bank Sta=388.2,403.2
XS Rating Curve= 0 ,0
Exp/Cntr=0.3,0.1

Type RM Length L Ch R = 1 ,9259.2  ,250.6,254.1,257.4
XS GIS Cut Line= 2
     2104779.581      427003.651     2105235.687      427072.824
#Sta/Elev= 20
       0 2960.04   100.3 2940.52   110.3 2938.53   130.4 2934.33   140.4    2933
   150.4 2932.72   170.5 2932.89   200.6 2932.89   240.7  2932.7   260.8  2932.7
   264.3 2932.78   270.8 2932.93   279.3 2933.55   290.8 2934.52   300.9 2935.27
     341 2938.06     351 2939.04     361 2940.32   391.1 2944.51   461.3 2953.98
#Mann= 3 , 0 , 0
       0      .1       0   264.3    .045       0   279.3      .1       0
Bank Sta=264.3,279.3
XS Rating Curve= 0 ,0
Exp/Cntr=0.3,0.1

Type RM Length L Ch R = 1 ,9005.2  ,96.2,99.2,102.3
XS GIS Cut Line= 2
     2104772.169      427207.629     2105194.498      427347.601
#Sta/Elev= 23
       0  2959.7    49.4 2950.35   108.8 2939.32   118.6 2937.81   128.5 2936.84
   138.4 2936.24   168.1  2934.7   182.8 2934.09   197.8  2933.6   217.5 2933.03
   227.4  2932.9     267 2932.78   306.5 2932.84   326.3 2932.74   336.2 2932.83
     346  2933.8   355.9 2936.34   365.8 2939.32   375.7 2941.41   395.5 2944.87
   415.3 2948.11   425.2 2949.64   444.9 2952.51
#Mann= 3 , 0 , 0
       0      .1       0   182.8    .045       0   197.8      .1       0
Bank Sta=182.8,197.8
XS Rating Curve= 0 ,0
Exp/Cntr=0.3,0.1

Type RM Length L Ch R = 1 ,8905.9  ,264.6,263,261.3
XS GIS Cut Line= 2
     2104760.863      427278.499     2105162.192      427470.566
#Sta/Elev= 25
       0 2960.72     9.9 2959.08    29.7 2955.24    39.6 2953.12    59.3 2948.62
      89 2941.22    98.9 2938.54   118.6 2932.74   128.5 2931.21   133.7 2931.13
   138.4 2931.07   148.7 2931.12   168.1 2931.82     178 2932.02   247.2 2932.99
   257.1 2933.25   276.8 2934.01   296.6 2934.91   306.5 2935.44   326.3 2936.72
   355.9 2938.87   385.6 2940.92   395.5 2941.91   425.2 2945.34   444.9 2947.52
#Mann= 3 , 0 , 0
       0      .1       0   133.7    .045       0   148.7      .1       0
Bank Sta=133.7,148.7
XS Rating Curve= 0 ,0
Exp/Cntr=0.3,0.1

Type RM Length L Ch R = 1 ,8643    ,308.5,291.3,274.1
XS GIS Cut Line= 2
     2104610.351      427510.312     2105038.978      427678.084
#Sta/Elev= 18
       0 2974.57      10  2971.7      20 2969.08      70 2957.32   110.1 2948.47
   130.1  2943.9   160.1 2936.86   170.1 2934.39   180.1 2931.69   190.1  2929.4
   199.9 2928.48   200.1 2928.45   210.1  2928.6   214.9 2928.79   390.2 2935.46
   400.2 2935.98   410.3 2936.62   460.3 2940.11
#Mann= 3 , 0 , 0
       0      .1       0   199.9    .045       0   214.9      .1       0
Bank Sta=199.9,214.9
XS Rating Curve= 0 ,0
Exp/Cntr=0.3,0.1

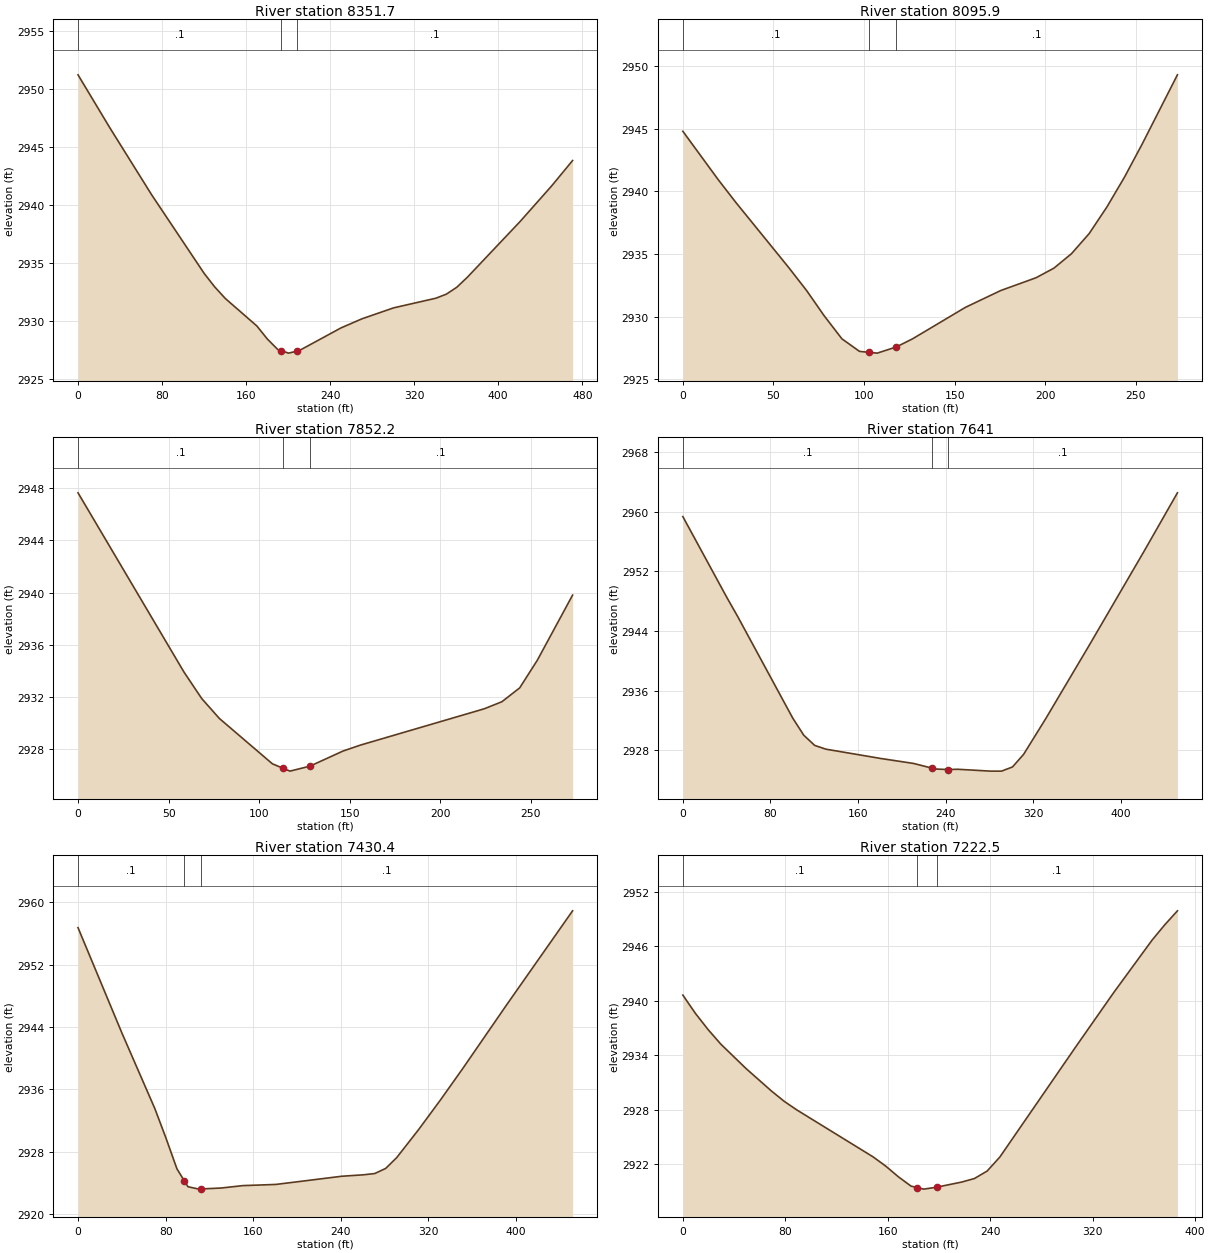
Type RM Length L Ch R = 1 ,8351.7  ,253.8,255.8,257.8
XS GIS Cut Line= 2
     2104647.802      427936.497     2105084.372      427760.226
#Sta/Elev= 23
       0 2951.24      30 2946.71    70.1 2940.88   120.2 2934.08   130.2 2932.92
   140.2 2931.93   170.3 2929.55   180.3 2928.42   190.3 2927.51   193.4 2927.42
   200.4 2927.21   208.4 2927.38   210.4 2927.42   250.4 2929.39   270.5 2930.18
   300.5 2931.12   340.6 2931.95   350.6  2932.3   360.6  2932.9   370.6 2933.76
   420.7 2938.56   450.8 2941.64   470.8 2943.84
#Mann= 3 , 0 , 0
       0      .1       0   193.4    .045       0   208.4      .1       0
Bank Sta=193.4,208.4
XS Rating Curve= 0 ,0
Exp/Cntr=0.3,0.1

Type RM Length L Ch R = 1 ,8095.9  ,247.4,243.7,240
XS GIS Cut Line= 2
     2104798.015      428136.087     2105058.732      428055.039
#Sta/Elev= 22
       0 2944.78    19.5 2940.93    29.2 2939.12    58.5 2933.91    68.3 2932.09
      78 2930.08    87.8 2928.24    97.5 2927.24   102.8 2927.16   107.3  2927.1
   117.8 2927.59   126.8 2928.24     156 2930.75   175.5 2932.09     195 2933.11
   204.8 2933.87   214.5 2935.02   224.3 2936.63     234 2938.73   243.8 2941.13
   253.5 2943.75     273 2949.28
#Mann= 3 , 0 , 0
       0      .1       0   102.8    .045       0   117.8      .1       0
Bank Sta=102.8,117.8
XS Rating Curve= 0 ,0
Exp/Cntr=0.3,0.1

Type RM Length L Ch R = 1 ,7852.2  ,205.9,211.1,216.6
XS GIS Cut Line= 2
     2104860.887      428389.352     2105105.882      428268.856
#Sta/Elev= 15
       0 2947.65    58.5 2933.91    68.3 2931.88      78 2930.36   107.3 2926.88
     113 2926.55     117 2926.32     128  2926.7   146.3 2927.86     156 2928.32
   224.3  2931.1     234 2931.64   243.8  2932.7   253.5 2934.81     273 2939.81
#Mann= 3 , 0 , 0
       0      .1       0     113    .045       0     128      .1       0
Bank Sta=113,128
XS Rating Curve= 0 ,0
Exp/Cntr=0.3,0.1

Type RM Length L Ch R = 1 ,7641    ,209.9,210.6,210.8
XS GIS Cut Line= 2
     2104853.077      428555.711     2105294.052      428458.437
#Sta/Elev= 21
       0 2959.35    40.1 2948.52    50.2 2945.91   100.4  2932.3   110.4 2930.02
   120.4 2928.65   130.5 2928.15   180.6  2926.9   210.7 2926.23   227.5  2925.6
   230.8 2925.48   242.5 2925.41   250.9 2925.45     281  2925.2     291  2925.2
     301 2925.76   311.1 2927.44   331.2  2932.2   371.3 2942.14   421.5 2954.79
   451.6 2962.54
#Mann= 3 , 0 , 0
       0      .1       0   227.5    .045       0   242.5      .1       0
Bank Sta=227.5,242.5
XS Rating Curve= 0 ,0
Exp/Cntr=0.3,0.1

Type RM Length L Ch R = 1 ,7430.4  ,211.9,208,203.9
XS GIS Cut Line= 2
     2104859.562      428678.924     2105300.537       428581.65
#Sta/Elev= 22
       0 2956.74    40.1 2943.23    70.2 2933.53    80.3 2929.77    90.3 2925.83
    96.9 2924.32   100.4 2923.53   110.4 2923.22   111.9 2923.24   130.5 2923.36
   150.5 2923.67   180.6 2923.82   240.8 2924.87   260.9 2925.06     271 2925.22
     281 2925.88     291 2927.26   311.1 2930.87   331.2  2934.7   351.2 2938.66
   391.4 2946.85   451.6  2958.9
#Mann= 3 , 0 , 0
       0      .1       0    96.9    .045       0   111.9      .1       0
Bank Sta=96.9,111.9
XS Rating Curve= 0 ,0
Exp/Cntr=0.3,0.1

Type RM Length L Ch R = 1 ,7222.5  ,138.8,147.1,155.6
XS GIS Cut Line= 2
     2104920.088      428871.311      2105278.92      428728.642
#Sta/Elev= 24
       0 2940.64     9.9 2938.61    19.8 2936.83    29.7 2935.23    49.5 2932.53
    69.3 2930.06    79.2 2928.93    89.1 2927.98   148.5 2922.82   158.4  2921.8
   168.3 2920.62   178.2 2919.59   183.1 2919.43   188.1 2919.26   198.1 2919.47
   217.8 2920.04   227.7 2920.43   237.6 2921.25   247.5 2922.79   306.9 2934.96
   336.6 2940.95   366.4  2946.7   376.2 2948.37   386.2 2949.93
#Mann= 3 , 0 , 0
       0      .1       0   183.1    .045       0   198.1      .1       0
Bank Sta=183.1,198.1
XS Rating Curve= 0 ,0
Exp/Cntr=0.3,0.1

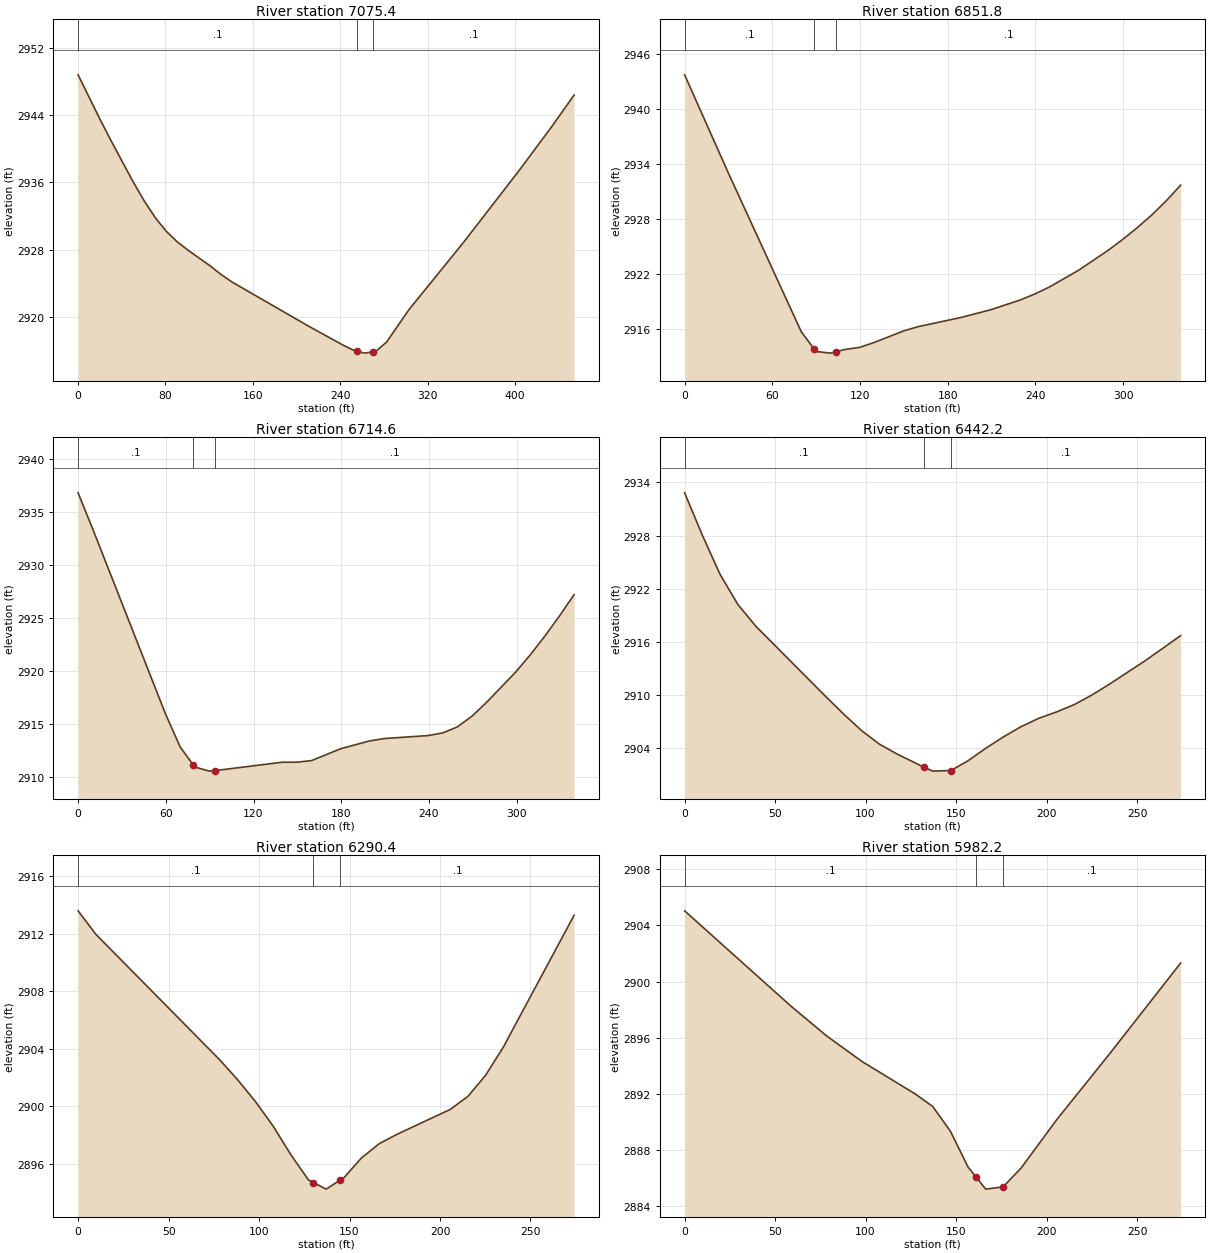
Type RM Length L Ch R = 1 ,7075.4  ,235,223.6,212
XS GIS Cut Line= 2
     2104898.471       428936.16     2105352.416      428929.675
#Sta/Elev= 25
       0 2948.76    20.2 2943.45    30.3 2940.92    50.4 2936.07    60.5 2933.82
    70.6 2931.83    80.7 2930.21    90.8 2928.95   100.9 2927.94   121.1 2926.09
   131.2 2925.05   141.2 2924.17   211.9 2918.89   242.1 2916.74   252.2  2916.1
   255.3    2916   262.3 2915.76   270.3 2915.92   272.4 2915.96   282.5 2917.09
   302.7 2920.89   353.1 2928.94   403.6  2937.4   433.8 2942.66     454 2946.36
#Mann= 3 , 0 , 0
       0      .1       0   255.3    .045       0   270.3      .1       0
Bank Sta=255.3,270.3
XS Rating Curve= 0 ,0
Exp/Cntr=0.3,0.1

Type RM Length L Ch R = 1 ,6851.8  ,137.2,137.2,137.2
XS GIS Cut Line= 2
      2104996.41      429160.377      2105299.04        429006.9
#Sta/Elev= 24
       0  2943.7    29.9 2933.02    79.8 2915.74    88.8 2913.81    89.8 2913.59
    99.8 2913.41   103.8 2913.57   109.8 2913.81   119.8 2914.04   129.7 2914.57
   149.7 2915.82   159.7 2916.29   189.6 2917.31   209.6 2918.14   229.5 2919.19
   239.5 2919.84   249.5  2920.6   269.5 2922.43   289.4 2924.56   299.4 2925.75
   309.4 2927.03   319.4 2928.42   329.3 2929.96   339.3 2931.69
#Mann= 3 , 0 , 0
       0      .1       0    88.8    .045       0   103.8      .1       0
Bank Sta=88.8,103.8
XS Rating Curve= 0 ,0
Exp/Cntr=0.3,0.1

Type RM Length L Ch R = 1 ,6714.6  ,266,272.4,278.7
XS GIS Cut Line= 2
      2105059.62      429281.833      2105362.25      429128.356
#Sta/Elev= 24
       0 2936.78      10 2933.38    59.9 2915.92    69.9 2912.83    78.8 2911.15
    79.8 2910.96    89.8 2910.57    93.8 2910.62   139.7 2911.41   149.7 2911.41
   159.7 2911.56   179.6 2912.68   199.6 2913.42   209.6 2913.64   239.5 2913.92
   249.5 2914.17   259.5 2914.74   269.5 2915.75   279.4 2917.04   299.4 2919.91
   309.4 2921.53   319.4 2923.31   329.3 2925.18   339.3 2927.19
#Mann= 3 , 0 , 0
       0      .1       0    78.8    .045       0    93.8      .1       0
Bank Sta=78.8,93.8
XS Rating Curve= 0 ,0
Exp/Cntr=0.3,0.1

Type RM Length L Ch R = 1 ,6442.2  ,151.8,151.8,151.8
XS GIS Cut Line= 2
     2105106.482      429515.903     2105375.629      429463.859
#Sta/Elev= 24
       0 2932.83     9.8 2928.04    19.6 2923.62    29.4 2920.23    39.2  2917.8
    78.3 2909.76    88.1  2907.8    97.9 2905.96   107.7 2904.44   117.5 2903.32
   132.2 2901.85   137.1  2901.4   147.2 2901.47   156.6 2902.57   166.4 2903.98
   176.2 2905.27     186 2906.43   195.8 2907.37   205.6 2908.09   215.4 2908.92
   225.2 2910.01     235 2911.25   254.6 2913.88   274.1  2916.7
#Mann= 3 , 0 , 0
       0      .1       0   132.2    .045       0   147.2      .1       0
Bank Sta=132.2,147.2
XS Rating Curve= 0 ,0
Exp/Cntr=0.3,0.1

Type RM Length L Ch R = 1 ,6290.4  ,308.3,308.2,308.2
XS GIS Cut Line= 2
     2105167.238      429653.573     2105436.385      429601.529
#Sta/Elev= 20
       0  2913.6     9.8 2911.97    78.3 2903.23    88.1 2901.86    97.9 2900.35
   107.7 2898.64   117.5 2896.65   127.3 2894.88     130  2894.7   137.1 2894.24
     145 2894.88   146.9 2895.03   156.6 2896.41   166.4  2897.4   176.2 2898.05
   205.6 2899.78   215.4 2900.69   225.2 2902.16     235 2904.12   274.1 2913.29
#Mann= 3 , 0 , 0
       0      .1       0     130    .045       0     145      .1       0
Bank Sta=130,145
XS Rating Curve= 0 ,0
Exp/Cntr=0.3,0.1

Type RM Length L Ch R = 1 ,5982.2  ,187.4,201.6,215.8
XS GIS Cut Line= 2
     2105224.193      429948.117      2105493.34      429896.073
#Sta/Elev= 15
       0 2905.04    58.7 2898.26    78.3 2896.15    97.9 2894.32   127.3 2892.01
   137.1 2891.11   146.9 2889.34   156.6  2886.8     161 2886.09   166.4 2885.22
     176 2885.38     186 2886.73   205.6 2890.16     235 2894.88   274.1 2901.32
#Mann= 3 , 0 , 0
       0      .1       0     161    .045       0     176      .1       0
Bank Sta=161,176
XS Rating Curve= 0 ,0
Exp/Cntr=0.3,0.1

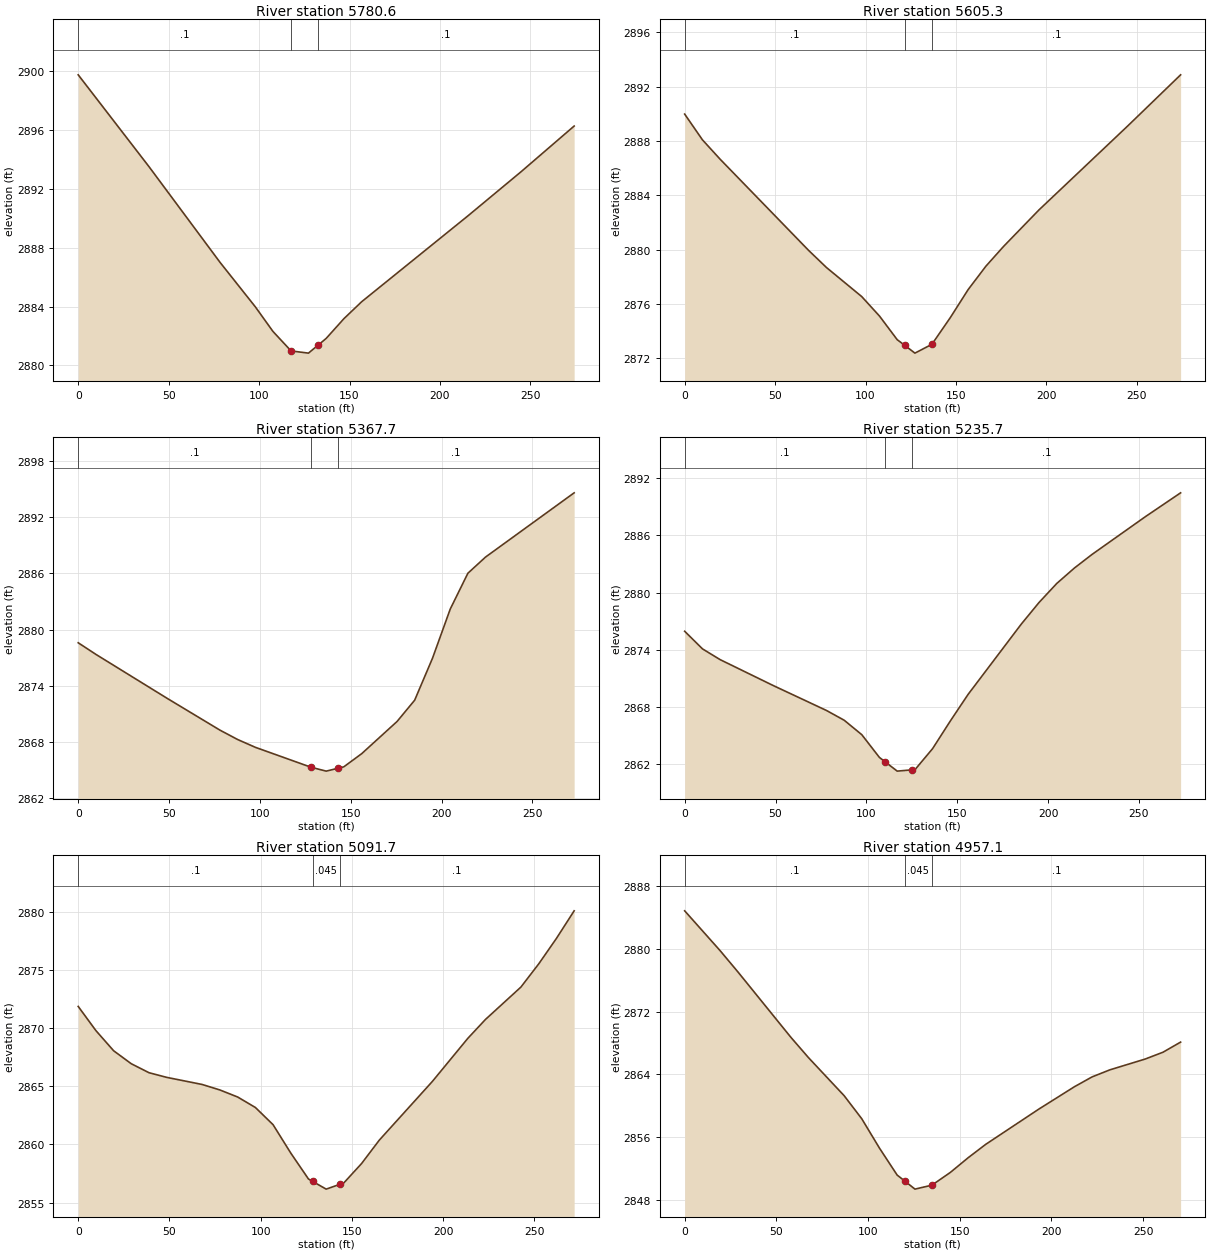
Type RM Length L Ch R = 1 ,5780.6  ,178,175.3,172.5
XS GIS Cut Line= 3
     2105226.935      430053.184     2105353.678      430105.514
     2105480.202      430158.367
#Sta/Elev= 14
       0 2899.75    39.2  2893.5    78.4 2887.01    97.9 2883.99   107.7 2882.31
   117.7 2880.99   127.3 2880.84   132.7 2881.39   137.1 2881.84   146.9 2883.18
   156.7 2884.33   215.5 2890.17   244.9 2893.17   274.2 2896.27
#Mann= 3 , 0 , 0
       0      .1       0   117.7    .045       0   132.7      .1       0
Bank Sta=117.7,132.7
XS Rating Curve= 0 ,0
Exp/Cntr=0.3,0.1

Type RM Length L Ch R = 1 ,5605.3  ,226.7,237.7,248.7
XS GIS Cut Line= 3
     2105175.887      430233.979      2105308.25      430269.787
     2105440.462      430306.142
#Sta/Elev= 18
       0 2889.98     9.8 2888.09    19.6 2886.66    68.6 2879.94    78.4 2878.69
    97.9 2876.55   107.7 2875.12   117.5 2873.38   121.7 2872.96   127.3 2872.39
   136.7 2873.04   146.9 2875.01   156.7 2877.06   166.5 2878.78   176.3 2880.24
   195.9 2882.93   244.9  2889.1   274.2 2892.87
#Mann= 3 , 0 , 0
       0      .1       0   121.7    .045       0   136.7      .1       0
Bank Sta=121.7,136.7
XS Rating Curve= 0 ,0
Exp/Cntr=0.3,0.1

Type RM Length L Ch R = 1 ,5367.7  ,131.9,132,132
XS GIS Cut Line= 3
     2105120.836      430388.596     2105221.124      430481.197
     2105321.028      430574.211
#Sta/Elev= 18
       0 2878.58     9.8 2877.33    48.8 2872.65      78 2869.23    87.8 2868.22
    97.5 2867.39   128.1 2865.26   136.5 2864.84   143.1 2865.15   146.2  2865.3
     156  2866.7   175.5 2870.15   185.2 2872.43     195 2876.91   204.8 2882.19
   214.5 2886.02   224.2 2887.75     273 2894.63
#Mann= 3 , 0 , 0
       0      .1       0   128.1    .045       0   143.1      .1       0
Bank Sta=128.1,143.1
XS Rating Curve= 0 ,0
Exp/Cntr=0.3,0.1

Type RM Length L Ch R = 1 ,5235.7  ,150,144,138.1
XS GIS Cut Line= 3
     2105047.341       430498.84     2105147.628      430591.441
     2105247.532      430684.454
#Sta/Elev= 22
       0 2875.93     9.8 2874.08    19.5 2872.95    48.8 2870.22      78 2867.61
    87.8 2866.58    97.5 2865.06   107.2 2862.67   110.4  2862.2     117 2861.23
   125.4 2861.37   126.8 2861.39   136.5  2863.6   146.2 2866.49     156 2869.29
   185.2 2876.66     195 2878.94   204.8 2880.95   214.5 2882.57   224.2    2884
   253.5 2887.96     273 2890.48
#Mann= 3 , 0 , 0
       0      .1       0   110.4    .045       0   125.4      .1       0
Bank Sta=110.4,125.4
XS Rating Curve= 0 ,0
Exp/Cntr=0.3,0.1

Type RM Length L Ch R = 1 ,5091.7  ,128.8,134.6,140.4
XS GIS Cut Line= 3
      2104955.56      430645.854     2105075.459      430709.792
     2105195.091      430774.225
#Sta/Elev= 26
       0 2871.87     9.7 2869.79    19.4 2868.06    29.1 2866.94    38.8 2866.17
    48.5 2865.77    67.9 2865.16    77.6 2864.69    87.4 2864.08    97.1 2863.18
   106.8  2861.7   116.5 2859.26   126.2 2857.03   128.5 2856.82   135.9 2856.16
   143.5 2856.58   145.6  2856.7   155.3 2858.36     165 2860.37   194.1 2865.42
   213.5 2869.12   223.2 2870.75   242.6 2873.53   252.4 2875.53   262.1 2877.72
   271.8 2880.09
#Mann= 3 , 0 , 0
       0      .1       0   128.5    .045       0   143.5      .1       0
Bank Sta=128.5,143.5
XS Rating Curve= 0 ,0
Exp/Cntr=0.3,0.1

Type RM Length L Ch R = 1 ,4957.1  ,144.3,146.1,147.9
XS GIS Cut Line= 3
     2104906.189      430734.305     2105005.567      430826.066
     2105104.563      430918.235
#Sta/Elev= 22
       0 2884.84    19.3 2879.77      29 2877.06      58 2868.69    67.6  2866.1
      87 2861.26    96.6 2858.32   106.3 2854.56   115.9 2851.14   119.9 2850.41
   125.6 2849.35   134.9 2849.86   144.9 2851.48   154.6 2853.35   164.2 2855.06
   193.2 2859.56   212.6 2862.41   222.2 2863.66   231.9 2864.56   251.2 2865.94
   260.9 2866.81   270.5  2868.1
#Mann= 3 , 0 , 0
       0      .1       0   119.9    .045       0   134.9      .1       0
Bank Sta=119.9,134.9
XS Rating Curve= 0 ,0
Exp/Cntr=0.3,0.1

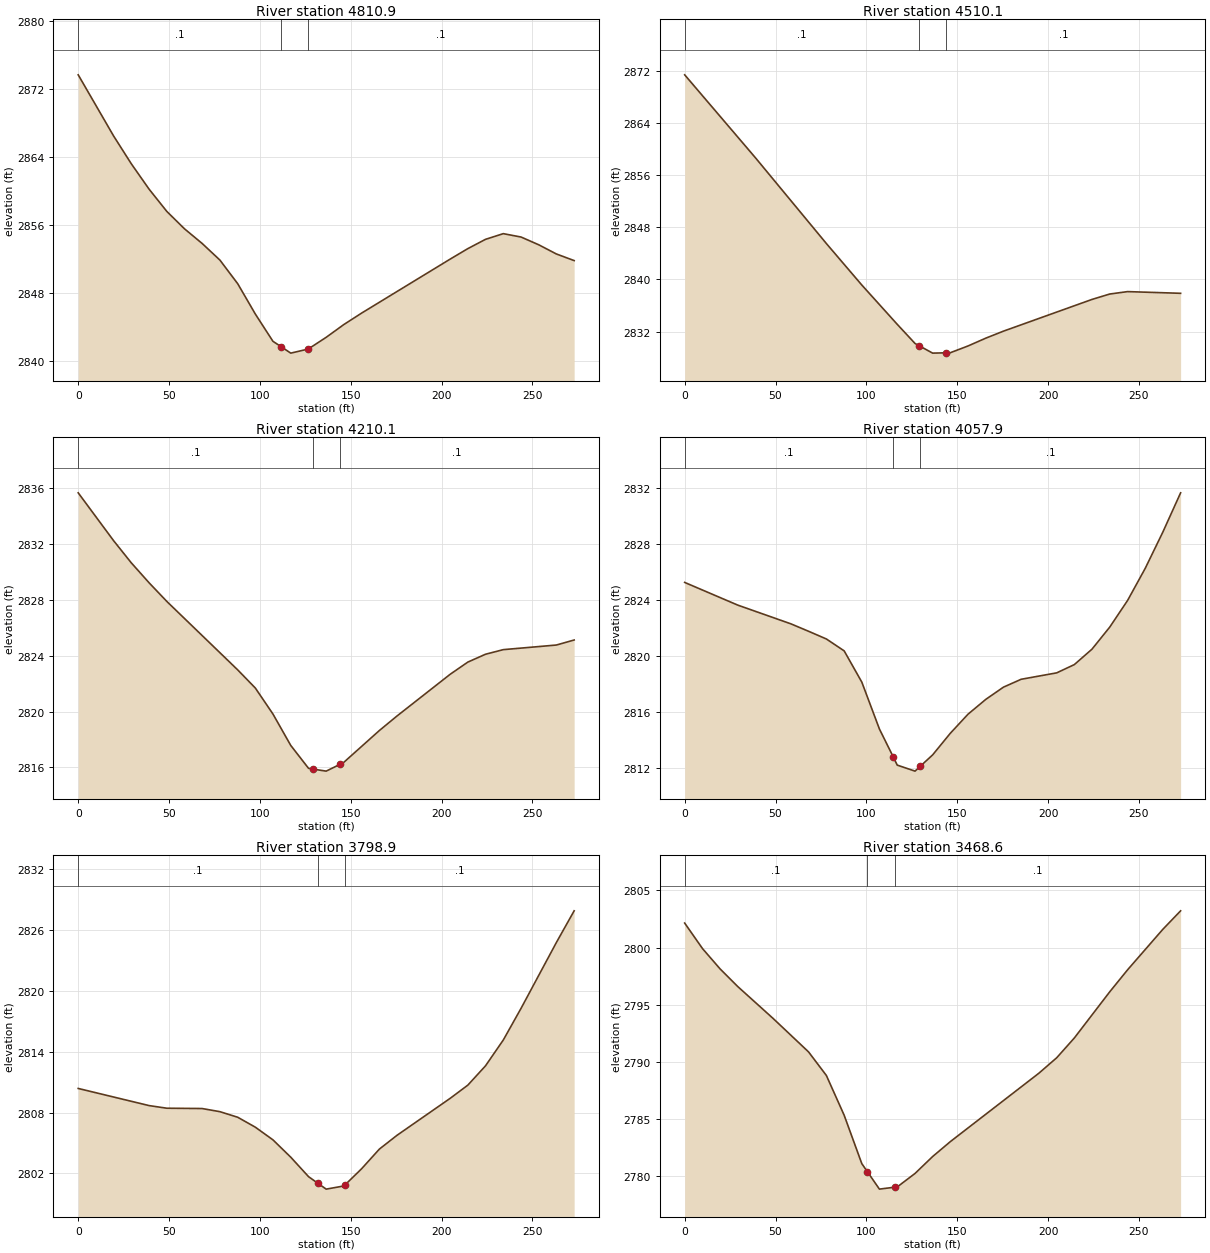
Type RM Length L Ch R = 1 ,4810.9  ,300.9,300.8,300.8
XS GIS Cut Line= 2
      2104829.29      430848.686     2105014.606      431049.154
#Sta/Elev= 25
       0 2873.64    19.5 2866.44    29.2 2863.18      39 2860.19    48.8 2857.56
    58.5 2855.52    68.2  2853.8      78 2851.84    87.8 2849.06    97.5 2845.49
   107.2 2842.28   111.6 2841.66     117 2840.89   126.6 2841.37   136.5 2842.75
   146.2 2844.25     156  2845.6   204.8 2851.96   214.5 2853.19   224.2 2854.28
     234 2854.95   243.8 2854.55   253.5 2853.64   263.2 2852.56     273 2851.78
#Mann= 3 , 0 , 0
       0      .1       0   111.6    .045       0   126.6      .1       0
Bank Sta=111.6,126.6
XS Rating Curve= 0 ,0
Exp/Cntr=0.3,0.1

Type RM Length L Ch R = 1 ,4510.1  ,303.6,300,296.4
XS GIS Cut Line= 3
     2104608.997       431052.33     2104701.654      431152.563
     2104794.312      431252.797
#Sta/Elev= 17
       0 2871.37      39 2858.64      78 2845.51    97.5 2839.15     117 2833.13
   126.8 2830.19     129 2829.85   136.5 2828.71     144 2828.76   146.2 2828.77
     156 2829.81   165.8 2831.01   175.5 2832.08   224.2 2836.94     234 2837.77
   243.8 2838.14     273 2837.88
#Mann= 3 , 0 , 0
       0      .1       0     129    .045       0     144      .1       0
Bank Sta=129,144
XS Rating Curve= 0 ,0
Exp/Cntr=0.3,0.1

Type RM Length L Ch R = 1 ,4210.1  ,158,152.2,146.3
XS GIS Cut Line= 2
     2104374.072      431271.819     2104588.649      431440.595
#Sta/Elev= 22
       0 2835.66    19.5 2832.23    29.2 2830.65      39 2829.22    48.8 2827.88
    87.8 2822.98    97.5 2821.68   107.2 2819.82     117 2817.57   126.8 2815.93
     129 2815.88   136.5 2815.73     144 2816.21   146.2 2816.36   165.8 2818.64
   175.5 2819.68   204.8 2822.67   214.5 2823.54   224.2  2824.1     234 2824.43
   263.2 2824.76     273 2825.12
#Mann= 3 , 0 , 0
       0      .1       0     129    .045       0     144      .1       0
Bank Sta=129,144
XS Rating Curve= 0 ,0
Exp/Cntr=0.3,0.1

Type RM Length L Ch R = 1 ,4057.9  ,245.9,259,272.2
XS GIS Cut Line= 2
     2104310.112       431447.08     2104561.253       431554.12
#Sta/Elev= 26
       0 2825.28    29.2 2823.66    58.5 2822.32    68.2 2821.79      78 2821.24
    87.8 2820.39    97.5 2818.16   107.2 2814.81   114.8 2812.82     117 2812.23
   126.8  2811.8   129.8 2812.16   136.5 2812.96   146.2  2814.5     156 2815.87
   165.8 2816.93   175.5  2817.8   185.2 2818.36   204.8 2818.82   214.5 2819.41
   224.2 2820.51     234 2822.09   243.8 2823.99   253.5 2826.28   263.2 2828.87
     273 2831.68
#Mann= 3 , 0 , 0
       0      .1       0   114.8    .045       0   129.8      .1       0
Bank Sta=114.8,129.8
XS Rating Curve= 0 ,0
Exp/Cntr=0.3,0.1

Type RM Length L Ch R = 1 ,3798.9  ,335.9,330.3,324.7
XS GIS Cut Line= 3
     2104242.989      431606.866     2104318.348      431720.679
     2104393.706      431834.492
#Sta/Elev= 24
       0 2810.38      39 2808.69    48.8 2808.43    68.2  2808.4      78 2808.09
    87.8 2807.54    97.5 2806.56   107.2 2805.31     117  2803.6   126.8 2801.68
   131.9 2801.03   136.5 2800.45   146.2 2800.76   146.9 2800.87     156 2802.46
   165.8  2804.4   175.5 2805.76   204.8 2809.41   214.5 2810.71   224.2 2812.61
     234 2815.16   243.8 2818.29   263.2 2824.77     273  2827.9
#Mann= 3 , 0 , 0
       0      .1       0   131.9    .045       0   146.9      .1       0
Bank Sta=131.9,146.9
XS Rating Curve= 0 ,0
Exp/Cntr=0.3,0.1

Type RM Length L Ch R = 1 ,3468.6  ,163.8,167.4,171
XS GIS Cut Line= 3
     2103988.223      431862.304     2104089.213      431954.136
     2104190.204      432045.969
#Sta/Elev= 23
       0 2802.15     9.8 2799.92    19.5 2798.14    29.2  2796.6    48.8 2793.79
    68.2 2790.88      78 2788.82    87.8 2785.34    97.5 2781.11   100.6  2780.4
   107.2 2778.88   115.6 2779.05     117 2779.07   126.8 2780.25   136.5 2781.73
   146.2 2783.03     195 2789.02   204.8 2790.37   214.5  2792.1     234 2796.14
   243.8 2798.06   263.2  2801.6     273 2803.22
#Mann= 3 , 0 , 0
       0      .1       0   100.6    .045       0   115.6      .1       0
Bank Sta=100.6,115.6
XS Rating Curve= 0 ,0
Exp/Cntr=0.3,0.1

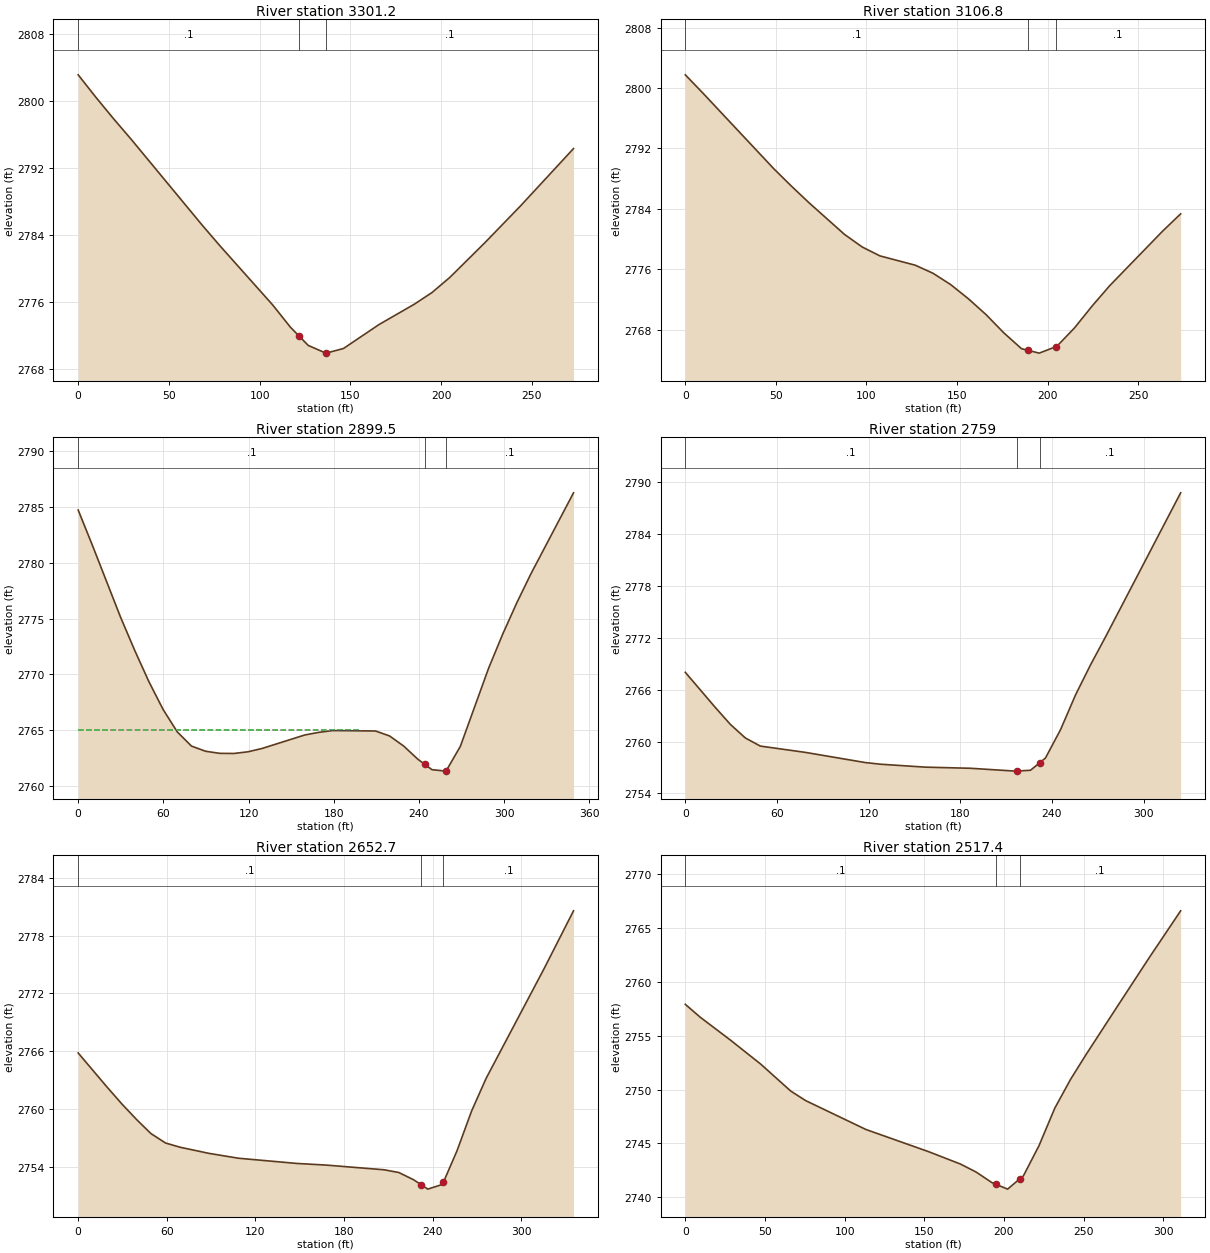
Type RM Length L Ch R = 1 ,3301.2  ,195.8,194.4,193
XS GIS Cut Line= 2
     2103871.174      431954.646      2104041.94      432167.644
#Sta/Elev= 20
       0  2803.1     9.8 2800.41    19.5 2797.86    29.2 2795.41    68.2  2785.2
      78 2782.73   107.2 2775.64     117 2772.98   121.8 2771.91   126.8 2770.81
   136.5 2769.89   136.8  2769.9   146.2 2770.44   165.8  2773.3   185.2 2775.72
     195 2777.12   204.8 2778.92   224.2 2783.08   243.8 2787.46     273  2794.3
#Mann= 3 , 0 , 0
       0      .1       0   121.8    .045       0   136.8      .1       0
Bank Sta=121.8,136.8
XS Rating Curve= 0 ,0
Exp/Cntr=0.3,0.1

Type RM Length L Ch R = 1 ,3106.8  ,211.3,207.3,203.2
XS GIS Cut Line= 2
     2103699.748      432062.057     2103883.087      432265.022
#Sta/Elev= 24
       0 2801.74     9.8  2799.3    48.8 2789.32    58.6    2787    68.4 2784.78
    87.9 2780.61    97.7 2778.94   107.4 2777.77     127 2776.53   136.8 2775.46
   146.5 2773.97   156.3 2772.09   166.1 2769.98   175.8 2767.59   185.6 2765.48
   189.4 2765.25   195.4 2764.89   204.4 2765.72   205.1 2765.78   214.9 2768.23
   224.7 2771.15   234.4 2773.84   263.7 2781.08   273.5 2783.33
#Mann= 3 , 0 , 0
       0      .1       0   189.4    .045       0   204.4      .1       0
Bank Sta=189.4,204.4
XS Rating Curve= 0 ,0
Exp/Cntr=0.3,0.1

Type RM Length L Ch R = 1 ,2899.5  ,138.3,140.5,142.8
XS GIS Cut Line= 2
     2103499.867      432213.122     2103776.082      432426.341
#Sta/Elev= 29
       0 2784.71      10 2781.56    29.9 2775.11    39.9 2772.13    49.8 2769.36
    59.8 2766.87    69.8 2764.86    79.8 2763.59    89.7 2763.13    99.7 2762.94
   109.7 2762.93   119.6 2763.08   129.6 2763.38   159.5 2764.58   169.5 2764.82
   179.4 2764.98   209.4 2764.94   219.3  2764.5   229.3 2763.59   239.3 2762.41
   244.1 2761.96   249.2 2761.48   259.1 2761.35   269.2 2763.57   289.1 2770.56
   299.1 2773.63   309.1 2776.45     319 2779.03   348.9 2786.25
#Mann= 3 , 0 , 0
       0      .1       0   244.1    .045       0   259.1      .1       0
#XS Ineff= 2 , 0
          199.45 2765.03
Permanent Ineff=
       F       F
Bank Sta=244.1,259.1
XS Rating Curve= 0 ,0
Exp/Cntr=0.3,0.1

Type RM Length L Ch R = 1 ,2759    ,103.1,106.3,109.6
XS GIS Cut Line= 2
     2103458.169      432329.424     2103693.839      432552.181
#Sta/Elev= 20
       0 2768.02    19.6 2763.96    29.5 2761.99    39.3 2760.42    49.1 2759.48
    78.6 2758.75   117.9 2757.57   127.8 2757.38   157.2 2757.04   186.7 2756.91
   216.2 2756.58   217.1 2756.59     226 2756.68   232.1 2757.56   235.8  2758.1
   245.7 2761.39   255.5 2765.41   265.3 2768.88   275.2 2772.15   324.3  2788.8
#Mann= 3 , 0 , 0
       0      .1       0   217.1    .045       0   232.1      .1       0
Bank Sta=217.1,232.1
XS Rating Curve= 0 ,0
Exp/Cntr=0.3,0.1

Type RM Length L Ch R = 1 ,2652.7  ,136.7,135.3,133.9
XS GIS Cut Line= 2
     2103408.129      432379.463     2103616.359      432642.575
#Sta/Elev= 23
       0  2765.8    19.7 2762.23    29.6  2760.5    39.5 2758.89    49.3 2757.42
    59.2 2756.44    69.1    2756    88.8 2755.36   108.6 2754.86     148 2754.32
   167.8 2754.15   207.2 2753.66   217.1 2753.38     227 2752.64   232.3 2752.11
   236.8 2751.65   246.7 2752.14   247.3 2752.34   256.6 2755.64   266.5 2759.78
   276.3 2763.16   315.8 2774.63   335.5 2780.57
#Mann= 3 , 0 , 0
       0      .1       0   232.3    .045       0   247.3      .1       0
Bank Sta=232.3,247.3
XS Rating Curve= 0 ,0
Exp/Cntr=0.3,0.1

Type RM Length L Ch R = 1 ,2517.4  ,89.1,94.6,100
XS GIS Cut Line= 3
     2103322.992      432452.993     2103374.165      432554.208
     2103504.547      432702.523
#Sta/Elev= 22
       0 2757.93     9.4 2756.73    28.4  2754.6    47.3 2752.38    66.2 2749.87
    75.6 2748.98   113.4  2746.3   152.9 2744.23   172.7 2743.09   182.5 2742.35
   192.4 2741.37   194.8 2741.22   202.3 2740.76   209.8  2741.7   212.2 2741.99
     222  2744.8   231.9 2748.28   241.8 2750.96   251.6 2753.28   271.4 2757.79
   291.1 2762.25   310.9 2766.62
#Mann= 3 , 0 , 0
       0      .1       0   194.8    .045       0   209.8      .1       0
Bank Sta=194.8,209.8
XS Rating Curve= 0 ,0
Exp/Cntr=0.3,0.1