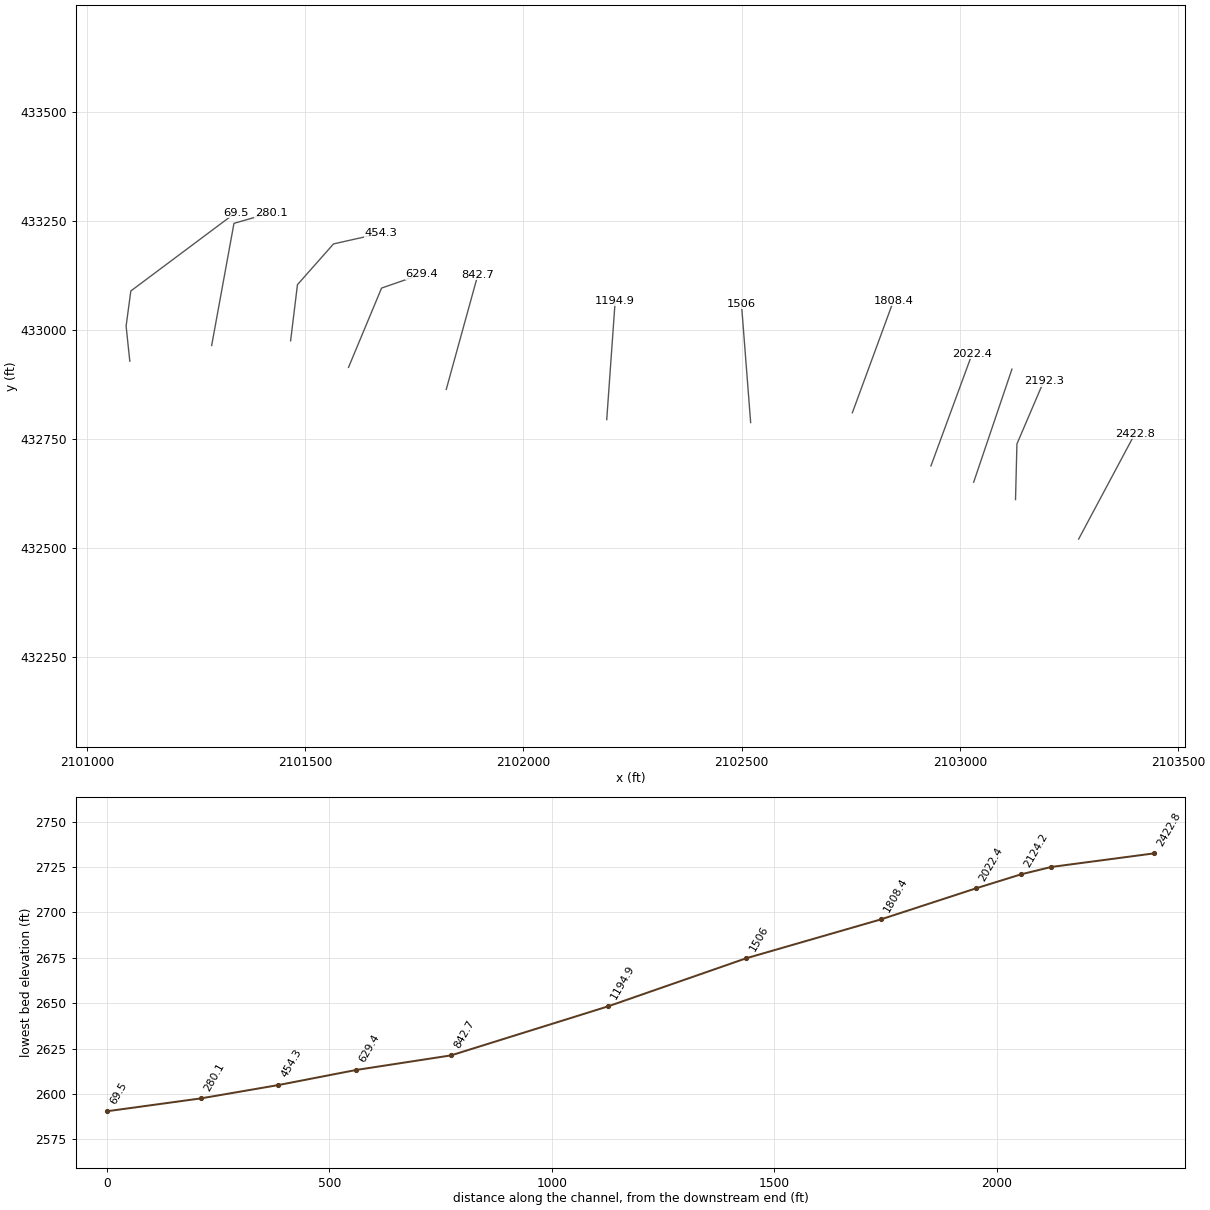
HEC-RAS study ImprvmntBr.prj: ImprvmntBr

--- ImprvmntBr.g01 (geometry) --- (continued)

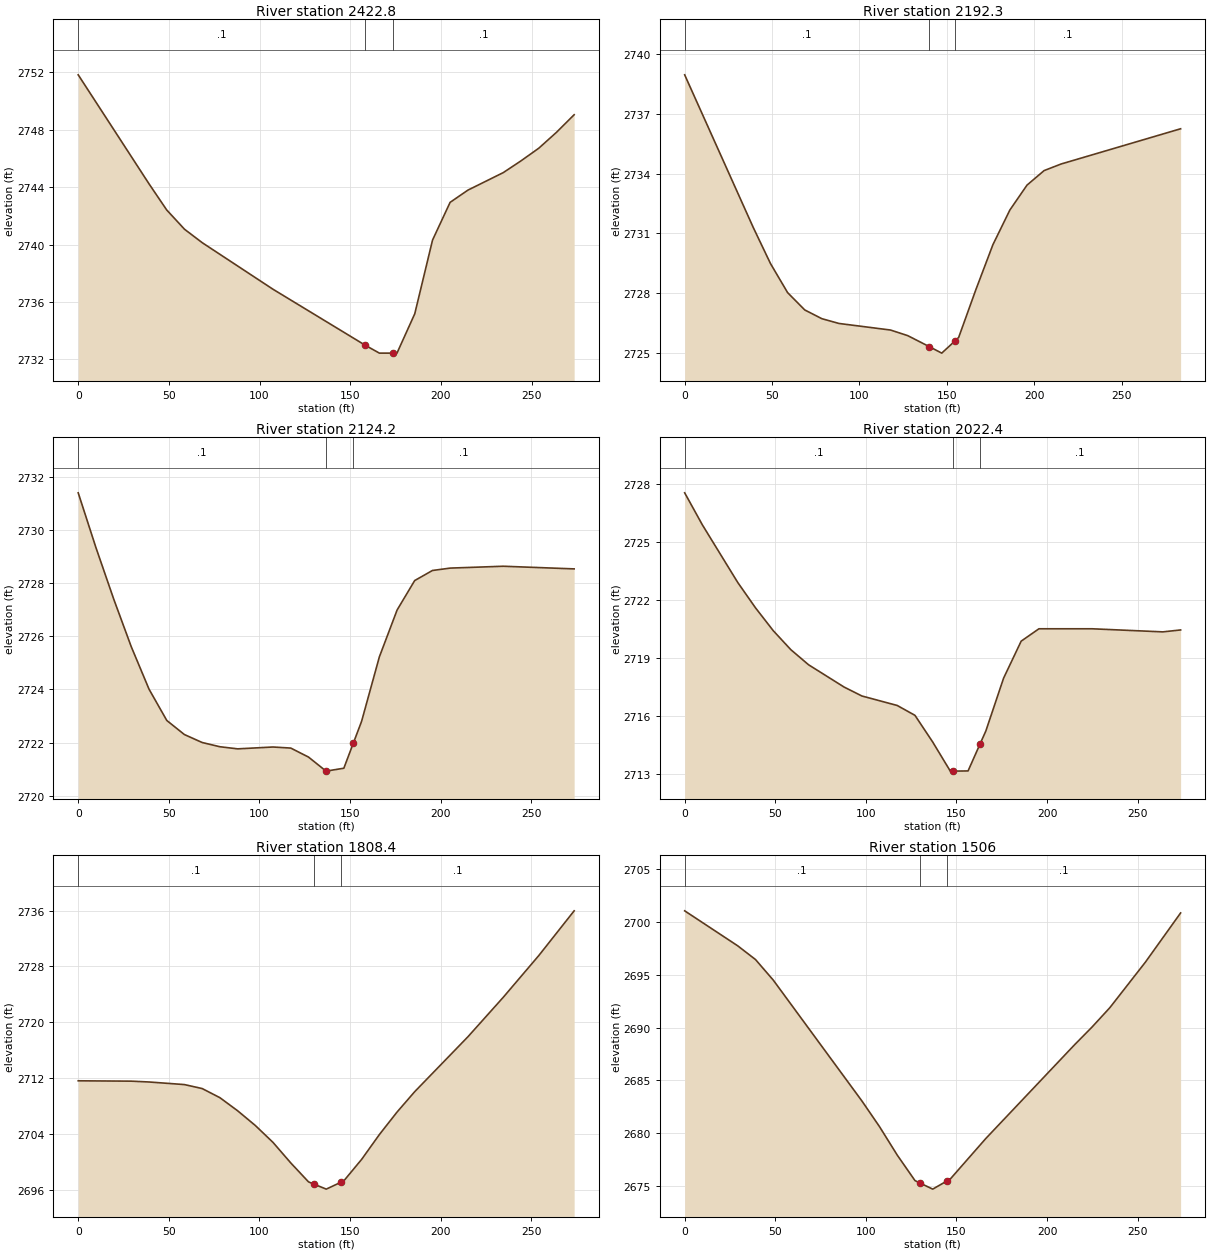
Type RM Length L Ch R = 1 ,2422.8  ,227.5,230.5,232.5
XS GIS Cut Line= 2
      2103271.88      432519.706     2103400.629      432761.018
#Sta/Elev= 19
       0 2751.82    39.1 2744.22    48.8 2742.41    58.6 2741.07    68.4 2740.13
   107.4 2736.89   158.4 2732.98   166.1 2732.44   173.4 2732.44   175.8 2732.44
   185.6 2735.18   195.4 2740.31   205.1 2742.94   214.9 2743.79   234.4 2745.01
   244.2 2745.83     254 2746.71   263.7 2747.81   273.5 2749.04
#Mann= 3 , 0 , 0
       0      .1       0   158.4    .045       0   173.4      .1       0
Bank Sta=158.4,173.4
XS Rating Curve= 0 ,0
Exp/Cntr=0.3,0.1

Type RM Length L Ch R = 1 ,2192.3  ,67.3,68,69.8
XS GIS Cut Line= 3
     2103127.261      432610.291      2103130.49      432737.812
     2103191.829      432881.474
#Sta/Elev= 20
       0 2738.96    39.2  2731.3    49.1 2729.48    58.9 2728.02    68.7 2727.15
    78.5 2726.71    88.3 2726.47   117.8 2726.14   127.6 2725.86   139.9 2725.31
   147.1 2724.98   154.9 2725.61   156.8 2725.77   166.6 2728.16   176.4 2730.43
   186.1 2732.17   195.9 2733.42   205.7 2734.15   215.4 2734.48   283.8 2736.25
#Mann= 3 , 0 , 0
       0      .1       0   139.9    .045       0   154.9      .1       0
Bank Sta=139.9,154.9
XS Rating Curve= 0 ,0
Exp/Cntr=0.3,0.1

Type RM Length L Ch R = 1 ,2124.2  ,102.4,101.8,101.2
XS GIS Cut Line= 2
     2103031.374      432650.106     2103119.058      432909.392
#Sta/Elev= 24
       0 2731.42     9.8 2729.35    19.6 2727.41    29.3 2725.61    39.1 2724.01
    48.9 2722.83    58.6  2722.3    68.4    2722    78.2 2721.84      88 2721.76
   107.5 2721.83   117.3 2721.79   127.1 2721.45   136.8 2720.92   146.6 2721.03
   151.8 2721.97   156.4  2722.8   166.2 2725.23     176    2727   185.7 2728.11
   195.5 2728.49   205.3 2728.58   234.6 2728.65   273.7 2728.55
#Mann= 3 , 0 , 0
       0      .1       0   136.8    .045       0   151.8      .1       0
Bank Sta=136.8,151.8
XS Rating Curve= 0 ,0
Exp/Cntr=0.3,0.1

Type RM Length L Ch R = 1 ,2022.4  ,214,214,214.1
XS GIS Cut Line= 2
     2102933.506      432687.483     2103027.834      432944.426
#Sta/Elev= 23
       0 2727.54     9.8 2725.88    29.3 2722.91    39.1  2721.6    48.9 2720.42
    58.6 2719.44    68.4 2718.66      88 2717.51    97.8 2717.05   117.3 2716.56
   127.1 2716.05   136.9 2714.67   146.6 2713.17   147.9 2713.17   156.4 2713.18
   162.9 2714.55   166.2 2715.24     176 2717.97   185.7 2719.88   195.5 2720.52
   224.8 2720.52   263.9 2720.36   273.7 2720.46
#Mann= 3 , 0 , 0
       0      .1       0   147.9    .045       0   162.9      .1       0
Bank Sta=147.9,162.9
XS Rating Curve= 0 ,0
Exp/Cntr=0.3,0.1

Type RM Length L Ch R = 1 ,1808.4  ,292.2,302.4,312.5
XS GIS Cut Line= 2
     2102753.467      432809.417     2102847.795       433066.36
#Sta/Elev= 23
       0 2711.59    29.3 2711.54    39.1 2711.42    58.6 2711.05    68.4 2710.48
    78.2 2709.17      88 2707.29    97.8 2705.17   107.5 2702.76   117.3 2699.82
   127.1  2697.1     130 2696.79   136.9 2696.06     145 2697.05   146.6 2697.25
   156.4 2700.32   166.2 2703.88     176 2707.12   185.7 2710.03   215.1 2717.91
   234.6 2723.57   254.2 2729.55   273.7 2735.96
#Mann= 3 , 0 , 0
       0      .1       0     130    .045       0     145      .1       0
Bank Sta=130,145
XS Rating Curve= 0 ,0
Exp/Cntr=0.3,0.1

Type RM Length L Ch R = 1 ,1506    ,314.5,311.1,307.8
XS GIS Cut Line= 2
     2102520.449       432786.95     2102499.313      433059.844
#Sta/Elev= 18
       0 2701.06    29.3 2697.74    39.1 2696.44    48.9 2694.49    97.8 2683.04
   107.5 2680.61   117.3 2677.91   127.1 2675.49   129.6 2675.28   136.9 2674.68
   144.6 2675.44   146.6 2675.64   166.2 2679.48   215.1 2688.35   224.8 2690.04
   234.6 2691.87   254.2 2696.18   273.7 2700.86
#Mann= 3 , 0 , 0
       0      .1       0   129.6    .045       0   144.6      .1       0
Bank Sta=129.6,144.6
XS Rating Curve= 0 ,0
Exp/Cntr=0.3,0.1

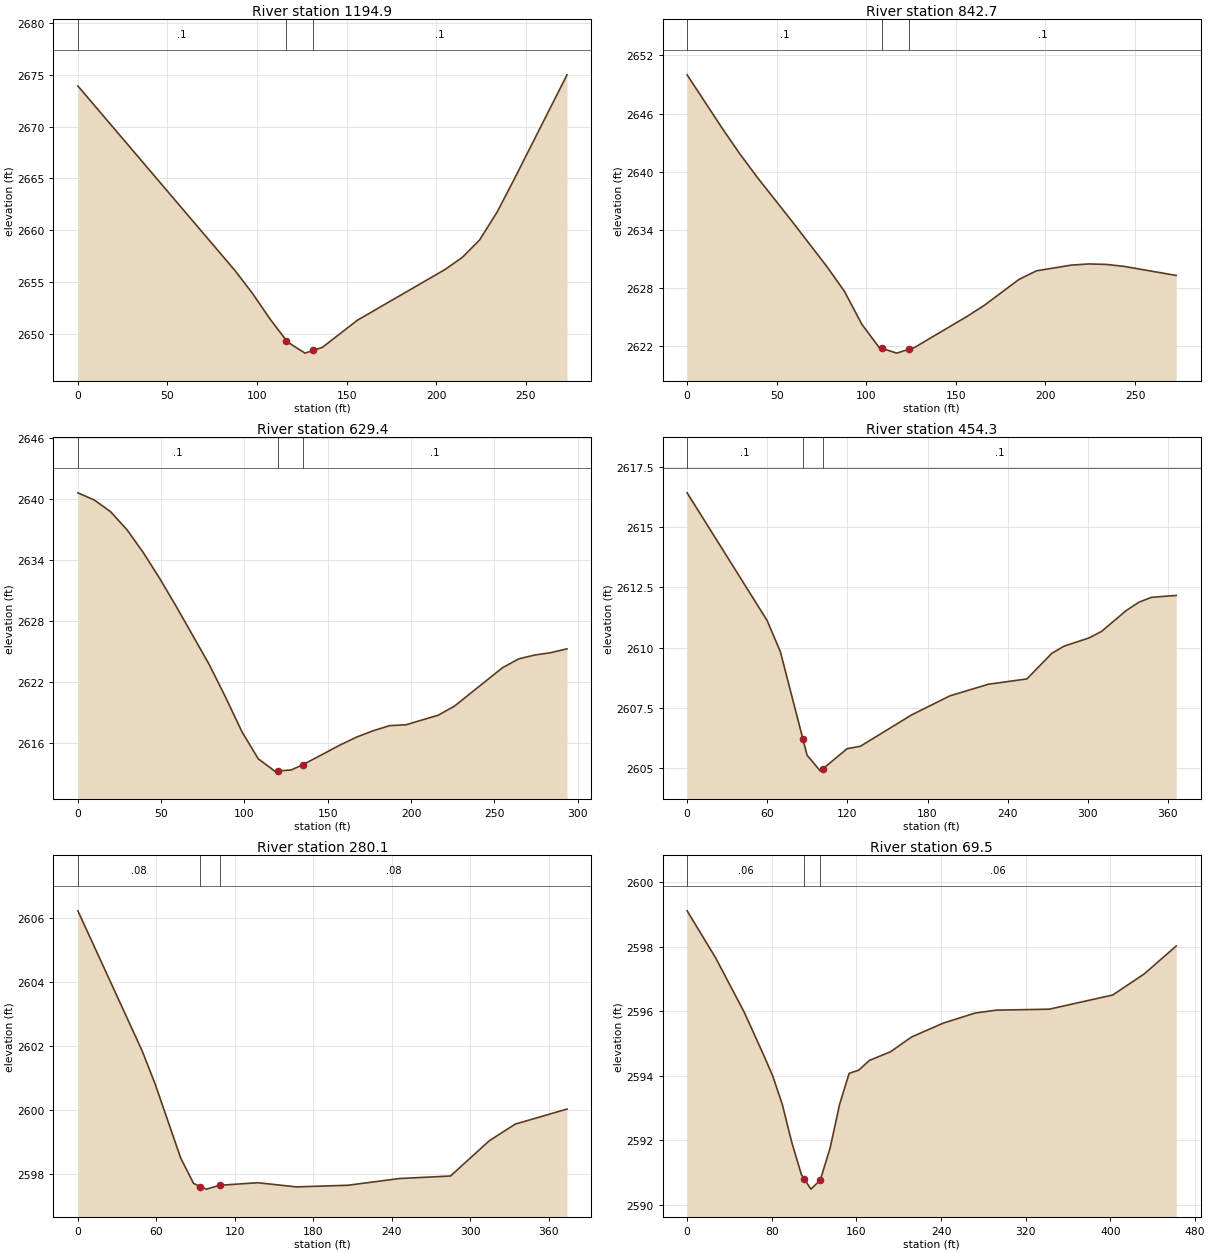
Type RM Length L Ch R = 1 ,1194.9  ,356.7,352.2,347.8
XS GIS Cut Line= 2
     2102190.744      432793.717     2102210.117      433066.029
#Sta/Elev= 16
       0 2673.92    87.8  2656.1    97.5 2653.91   107.2 2651.46   116.4 2649.37
     117 2649.23   126.8 2648.16   131.4 2648.43   136.5 2648.72     156 2651.33
   204.8 2656.21   214.5 2657.38   224.2 2659.07     234 2661.76   243.8 2665.02
     273 2674.99
#Mann= 3 , 0 , 0
       0      .1       0   116.4    .045       0   131.4      .1       0
Bank Sta=116.4,131.4
XS Rating Curve= 0 ,0
Exp/Cntr=0.3,0.1

Type RM Length L Ch R = 1 ,842.7   ,216.1,213.3,210.5
XS GIS Cut Line= 3
     2101823.064      432862.874     2101859.339      432994.466
     2101895.613      433126.058
#Sta/Elev= 22
       0    2650    19.5  2644.5    29.2 2641.89      39 2639.44    58.5 2634.87
      78 2630.18    87.8 2627.62    97.5 2624.22   107.2 2621.81   108.9 2621.71
     117 2621.23   123.9 2621.63   126.8  2621.8     156    2625   165.8 2626.16
   185.2 2628.85     195 2629.74   214.5 2630.33   224.2 2630.45     234  2630.4
   243.8  2630.2     273 2629.26
#Mann= 3 , 0 , 0
       0      .1       0   108.9    .045       0   123.9      .1       0
Bank Sta=108.9,123.9
XS Rating Curve= 0 ,0
Exp/Cntr=0.3,0.1

Type RM Length L Ch R = 1 ,629.4   ,168.9,175.1,181.2
XS GIS Cut Line= 3
     2101599.215      432913.475     2101674.902      433095.323
     2101766.143      433127.009
#Sta/Elev= 27
       0 2640.62     9.8 2639.92    19.7 2638.75    29.6 2636.96    39.4  2634.7
    49.2 2632.16    59.1 2629.41    78.8 2623.72    88.6  2620.5    98.5 2617.07
   108.3 2614.41   118.2  2613.2   119.9 2613.22     128 2613.31   134.9 2613.82
   157.6 2615.79   167.4 2616.56   177.3 2617.18   187.1 2617.68     197 2617.77
   216.3 2618.71     226  2619.6   254.9 2623.39   264.6 2624.26   274.2 2624.64
   283.9 2624.87   293.6 2625.25
#Mann= 3 , 0 , 0
       0      .1       0   119.9    .045       0   134.9      .1       0
Bank Sta=119.9,134.9
XS Rating Curve= 0 ,0
Exp/Cntr=0.3,0.1

Type RM Length L Ch R = 1 ,454.3   ,175.6,174.2,172.9
XS GIS Cut Line= 4
     2101466.515      432974.419     2101482.242      433103.187
     2101564.811      433196.568      2101673.92      433221.142
#Sta/Elev= 21
       0 2616.41    59.9 2611.12    69.8 2609.83    86.7 2606.21    89.8 2605.54
    99.8 2604.88   101.7 2604.98   119.8 2605.81   129.7 2605.91   168.1 2607.21
   196.8    2608   225.6 2608.48   254.4  2608.7     273 2609.76   282.3 2610.06
     301  2610.4   310.3 2610.67   328.9 2611.54   338.3 2611.88   347.6 2612.08
   366.2 2612.16
#Mann= 3 , 0 , 0
       0      .1       0    86.7    .045       0   101.7      .1       0
Bank Sta=86.7,101.7
XS Rating Curve= 0 ,0
Exp/Cntr=0.3,0.1

Type RM Length L Ch R = 1 ,280.1   ,209.5,210.6,211.7
XS GIS Cut Line= 3
      2101285.65      432963.606     2101336.764       433243.75
     2101422.282      433268.324
#Sta/Elev= 16
       0 2606.23    49.1 2601.86    58.9 2600.84    78.6 2598.51    88.4 2597.72
    93.5 2597.62    98.2 2597.54   108.5 2597.66   137.5 2597.74   166.9 2597.61
   206.2 2597.66   245.5 2597.87   284.8 2597.95   314.4 2599.05   334.2 2599.57
   373.8 2600.04
#Mann= 3 , 0 , 0
       0     .08       0    93.5    .045       0   108.5     .08       0
Bank Sta=93.5,108.5
XS Rating Curve= 0 ,0
Exp/Cntr=0.3,0.1

Type RM Length L Ch R = 1 ,69.5    ,65.5,69.5,73.4
XS GIS Cut Line= 4
     2101098.135      432927.642     2101089.646      433008.071
     2101100.457      433088.632     2101340.696      433268.324
#Sta/Elev= 25
       0 2599.11      27 2597.65    53.9 2595.97    71.9 2594.67    80.9 2593.99
    89.9 2593.11    98.9 2591.93     108 2590.93   110.8 2590.79     117 2590.48
   125.8 2590.76   135.1 2591.75   144.1 2593.11   153.1 2594.07   162.2 2594.17
   172.2 2594.47   192.2 2594.74   212.2  2595.2   242.2 2595.63   272.2 2595.94
   292.2 2596.03   342.2 2596.06   402.2  2596.5   432.2 2597.16   462.2 2598.02
#Mann= 3 , 0 , 0
       0     .06       0   110.8    .045       0   125.8     .06       0
Bank Sta=110.8,125.8
XS Rating Curve= 0 ,0
Exp/Cntr=0.3,0.1

Chan Stop Cuts=-1
Use User Specified Reach Order=0